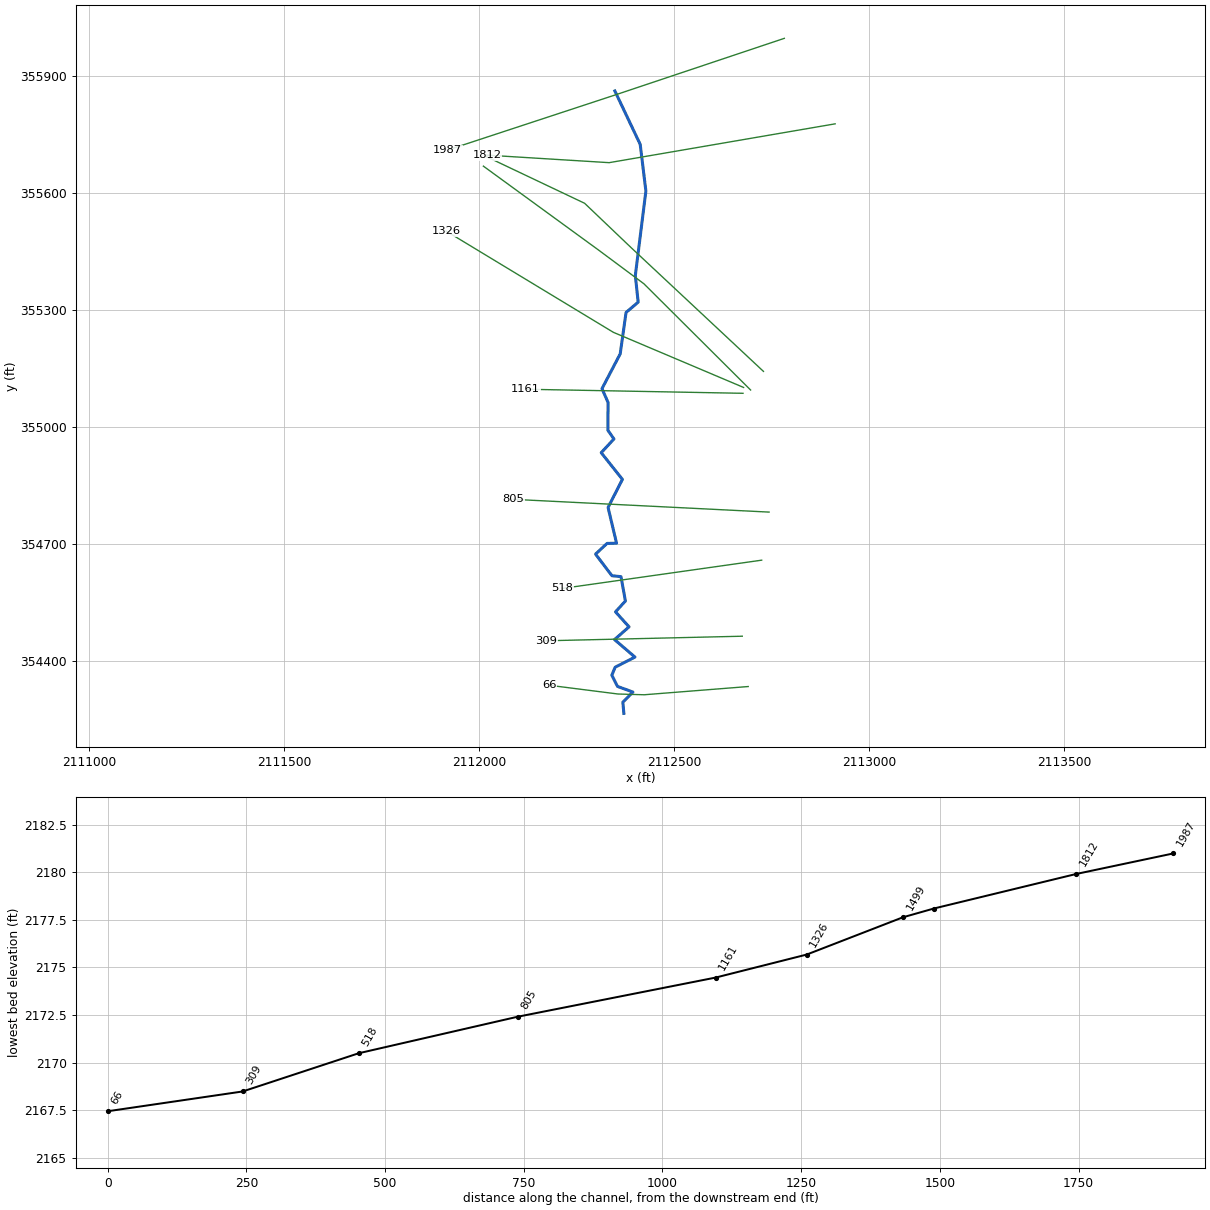
--- SNKNGCKT2.prj (project) ---

Proj Title=SNKNGCKT2
Current Plan=p01
Default Exp/Contr=0.3,0.1
English Units
Geom File=g01
Flow File=f01
Plan File=p01
Y Axis Title=Elevation
X Axis Title(PF)=Main Channel Distance
X Axis Title(XS)=Station
BEGIN DESCRIPTION:
Stream Name- Sinking Creek Tributary 2
Flood Zone: Zone A
Greenbrier County, WV
County-Wide Study
WVDHSEM-2018-3, Flood Risk Project
HEC-RAS Version: 5.0.7
General Notes:
For the Hydrology Regression was used.
END DESCRIPTION:
DSS Export Rating Curves= 0
DSS Export Rating Curve Sorted= 0
DSS Export Volume Flow Curves= 0
DXF Filename=SNKNGCKT2.F2.
DXF OffsetX= 0
DXF OffsetY= 0
DXF ScaleX= 1
DXF ScaleY= 10

--- SNKNGCKT2.p01 (plan) ---

Plan Title=Floodplain
Program Version=5.07
Short Identifier=Floodplain
Geom File=g01
Flow File=f01
Subcritical Flow
K Sum by GR= 0
Std Step Tol= 0.01
Critical Tol= 0.01
Num of Std Step Trials= 20
Max Error Tol= 0.3
Flow Tol Ratio= 0.001
Split Flow NTrial= 30
Split Flow Tol= 0.02
Split Flow Ratio= 0.02
Log Output Level= 0
Friction Slope Method= 1
Unsteady Friction Slope Method= 2
Unsteady Bridges Friction Slope Method= 1
Parabolic Critical Depth
Global Vel Dist= 0 , 0 , 0
Global Log Level= 0
CheckData=True
Encroach Param=-1 ,0,0, 0
Computation Interval=1MIN
Output Interval=1HOUR
Instantaneous Interval=1HOUR
Mapping Interval=1HOUR
Computation Time Step Use Courant=        0
Computation Time Step Use Time Series=    0
Computation Time Step Count To Double=0
Computation Time Step Max Doubling=0
Computation Time Step Max Halving=0
Computation Time Step Residence Courant=0
Run HTab= 0
Run UNet= 0
Run Sediment= 0
Run PostProcess= 0
Run WQNet= 0
Run RASMapper= 0
UNET Theta= 1
UNET Theta Warmup= 1
UNET ZTol= 0.02
UNET ZSATol= 0.02
UNET MxIter= 20
UNET Max Iter WO Improvement= 0
UNET MaxInSteps= 0
UNET DtIC= 0
UNET DtMin= 0
UNET MaxCRTS= 20
UNET WFStab= 2
UNET SFStab= 1
UNET WFX= 1
UNET SFX= 1
UNET 1D Methodology=Finite Difference
UNET DSS MLevel= 4
UNET Pardiso=0
UNET DZMax Abort= 100
UNET Use Existing IB Tables=-1
UNET Froude Reduction=False
UNET Froude Limit= 0.8
UNET Froude Power= 4
UNET D1 Cores= 0
UNET D2 Coriolis=0
UNET D2 Cores= 0
UNET D2 Theta= 1
UNET D2 Theta Warmup= 1
UNET D2 Z Tol= 0.01
UNET D2 Volume Tol= 0.01
UNET D2 Max Iterations= 20
UNET D2 Equation= 0
UNET D2 RampUpFraction=0.1
UNET D2 TimeSlices= 1
UNET D2 BCVolumeCheck=0
UNET D1D2 MaxIter= 0
UNET D1D2 ZTol=0.01
UNET D1D2 QTol=0.1
UNET D1D2 MinQTol=1
Write IC File= 0
Write IC File at Fixed DateTime=0
Write IC File at Sim End=0
Echo Input=False
Echo Parameters=False
Echo Output=False
Write Detailed= 0
HDF Write Warmup=0
HDF Write Time Slices=0
HDF Flush=0
HDF Face Node Velocities=0
HDF Compression= 1
HDF Chunk Size= 1
HDF Spatial Parts= 1
HDF Use Max Rows=0
HDF Fixed Rows= 1
Calibration Method= 0
Calibration Iterations= 20
Calibration Max Change=0.05
Calibration Tolerance=0.2
Calibration Maximum=1.5
Calibration Minimum=0.5
Calibration Optimization Method= 1
WQ AD Non Conservative
WQ ULTIMATE=-1
WQ Max Comp Step=1HOUR
WQ Output Interval=15MIN
WQ Output Selected Increments= 0
WQ Output face flow=0
WQ Output face velocity=0
WQ Output face area=0
WQ Output face dispersion=0
WQ Output cell volume=0
WQ Output cell surface area=0
WQ Output cell continuity=0
WQ Output cumulative cell continuity=0
WQ Output face conc=0
WQ Output face dconc_dx=0
WQ Output face courant=0
WQ Output face peclet=0
WQ Output face adv mass=0
WQ Output face disp mass=0
WQ Output cell mass=0
WQ Output cell source sink temp=0
WQ Output nsm pathways=0
WQ Output nsm derived pathways=0
WQ Output MaxMinRange=-1
WQ Daily Max Min Mean=-1
WQ Daily Range=0
WQ Daily Time=0
WQ Create Restart=0
WQ Fixed Restart=0
WQ System Summary=0
WQ Write To DSS=0
WQ Use Fixed Temperature=0
Sorting and Armoring Iterations= 10
XS Update Threshold= 0.02
Bed Roughness Predictor= 0
Hydraulics Update Threshold= 0.02
Energy Slope Method= 1
Volume Change Method= 1
Sediment Retention Method= 0
XS Weighting Method= 0
Number of US Weighted Cross Sections= 1
Number of DS Weighted Cross Sections= 1
Upstream XS Weight=0
Main XS Weight=1
Downstream XS Weight=0
Number of DS XS's Weighted with US Boundary= 1
Upstream Boundary Weight= 1
Weight of XSs Associated with US Boundary= 0
Number of US XS's Weighted with DS Boundary= 1
Downstream Boundary Weight= 0.5
Weight of XSs Associated with DS Boundary= 0.5
Percentile Method= 0
Sediment Output Level= 3
Mass or Volume Output= 0
Output Increment Type= 1
Profile and TS Output Increment= 1
XS Output Flag= 0
XS Output Increment= 10
Write Gradation File= 0
Read Gradation Hotstart= 0
Write HDF5 File= 1
Write Binary Output= 1
Write DSS Sediment File= 0
SV Curve= 0
Specific Gage Flag= 0

--- SNKNGCKT2.f01 (steady flow) ---

Flow Title=Flow
Program Version=5.07
Number of Profiles= 6
Profile Names=f1p,f10p,f4p,f2p,f02p,f1pplus
River Rch & RM=FLYNNCK,Main            ,9788
     547     289     384     463     765     810
River Rch & RM=FLYNNCK,Main            ,8346
     617     327     434     523     861     912
River Rch & RM=FLYNNCK,Main            ,2542
     689     367     486     584     959    1020
River Rch & RM=HUGHRTCK,Main            ,26252
     536     283     376     454     750     793
River Rch & RM=HUGHRTCK,Main            ,25696
     596     316     419     505     832     882
River Rch & RM=HUGHRTCK,Main            ,21314
     890     479     631     757    1230    1320
River Rch & RM=HUGHRTCK,Main            ,18981
     994     536     706     845    1370    1470
River Rch & RM=HUGHRTCK,Main            ,16952
    1100     599     786     940    1520    1630
River Rch & RM=HUGHRTCK,Main            ,13127
    1280     695     911    1090    1760    1890
River Rch & RM=HUGHRTCK,Main            ,7853
    2240    1250    1620    1920    3050    3320
River Rch & RM=HUGHRTCKT1,Main            ,3576
     413     215     288     348     580     610
River Rch & RM=SNKNGCKT1,Main            ,15927
     161    81.1     110     135     230     238
River Rch & RM=SNKNGCKT1,Main            ,15623
     182      92     125     153     260     269
River Rch & RM=SNKNGCKT1,Main            ,13637
     351     182     244     296     495     519
River Rch & RM=SNKNGCKT1,Main            ,12716
     412     215     287     348     579     609
River Rch & RM=SNKNGCKT1,Main            ,10019
     582     308     409     493     812     860
River Rch & RM=SNKNGCKT1,Main            ,8301
     724     386     511     614    1010    1070
River Rch & RM=SNKNGCKT1,Main            ,7842
     808     433     572     686    1120    1190
River Rch & RM=SNKNGCKT2,Main            ,1987
     171    86.1     117     143     244     253
River Rch & RM=SNKNGCKT2,Main            ,1326
     191    96.8     131     160     273     283
River Rch & RM=SNKNGCKT3,Main            ,1878
     154    77.6     106     129     221     228
River Rch & RM=SNKNGCKT3,Main            ,756
     172    86.8     118     144     246     255
River Rch & RM=SNKNGCKT4,Main            ,1795
    27.9    13.1    18.5      23    41.2    41.3
River Rch & RM=SNKNGCKT4,Main            ,1597
      33    15.6    21.9    27.3    48.7    48.8
River Rch & RM=SNKNGCKT4,Main            ,987
    39.5    18.8    26.3    32.7      58    58.4
River Rch & RM=STONYRN,Main            ,5205
     582     308     409     493     813     861
River Rch & RM=STONYRN,Main            ,3401
     666     354     469     565     928     985
Boundary for River Rch & Prof#=FLYNNCK,Main            , 1
Up Type= 0
Dn Type= 3
Dn Slope=0.009659
Boundary for River Rch & Prof#=FLYNNCK,Main            , 2
Up Type= 0
Dn Type= 3
Dn Slope=0.009659
Boundary for River Rch & Prof#=FLYNNCK,Main            , 3
Up Type= 0
Dn Type= 3
Dn Slope=0.009659
Boundary for River Rch & Prof#=FLYNNCK,Main            , 4
Up Type= 0
Dn Type= 3
Dn Slope=0.009659
Boundary for River Rch & Prof#=FLYNNCK,Main            , 5
Up Type= 0
Dn Type= 3
Dn Slope=0.009659
Boundary for River Rch & Prof#=FLYNNCK,Main            , 6
Up Type= 0
Dn Type= 3
Dn Slope=0.009659
Boundary for River Rch & Prof#=HUGHRTCK,Main            , 1
Up Type= 0
Dn Type= 3
Dn Slope=0.002151
Boundary for River Rch & Prof#=HUGHRTCK,Main            , 2
Up Type= 0
Dn Type= 3
Dn Slope=0.002151
Boundary for River Rch & Prof#=HUGHRTCK,Main            , 3
Up Type= 0
Dn Type= 3
Dn Slope=0.002151
Boundary for River Rch & Prof#=HUGHRTCK,Main            , 4
Up Type= 0
Dn Type= 3
Dn Slope=0.002151
Boundary for River Rch & Prof#=HUGHRTCK,Main            , 5
Up Type= 0
Dn Type= 3
Dn Slope=0.002151
Boundary for River Rch & Prof#=HUGHRTCK,Main            , 6
Up Type= 0
Dn Type= 3
Dn Slope=0.002151
Boundary for River Rch & Prof#=HUGHRTCKT1,Main            , 1
Up Type= 0
Dn Type= 3
Dn Slope=0.008324
Boundary for River Rch & Prof#=HUGHRTCKT1,Main            , 2
Up Type= 0
Dn Type= 3
Dn Slope=0.008324
Boundary for River Rch & Prof#=HUGHRTCKT1,Main            , 3
Up Type= 0
Dn Type= 3
Dn Slope=0.008324
Boundary for River Rch & Prof#=HUGHRTCKT1,Main            , 4
Up Type= 0
Dn Type= 3
Dn Slope=0.008324
Boundary for River Rch & Prof#=HUGHRTCKT1,Main            , 5
Up Type= 0
Dn Type= 3
Dn Slope=0.008324
Boundary for River Rch & Prof#=HUGHRTCKT1,Main            , 6
Up Type= 0
Dn Type= 3
Dn Slope=0.008324
Boundary for River Rch & Prof#=SNKNGCKT1,Main            , 1
Up Type= 0
Dn Type= 3
Dn Slope=0.003593
Boundary for River Rch & Prof#=SNKNGCKT1,Main            , 2
Up Type= 0
Dn Type= 3
Dn Slope=0.003593
Boundary for River Rch & Prof#=SNKNGCKT1,Main            , 3
Up Type= 0
Dn Type= 3
Dn Slope=0.003593
Boundary for River Rch & Prof#=SNKNGCKT1,Main            , 4
Up Type= 0
Dn Type= 3
Dn Slope=0.003593
Boundary for River Rch & Prof#=SNKNGCKT1,Main            , 5
Up Type= 0
Dn Type= 3
Dn Slope=0.003593
Boundary for River Rch & Prof#=SNKNGCKT1,Main            , 6
Up Type= 0
Dn Type= 3
Dn Slope=0.003593
Boundary for River Rch & Prof#=SNKNGCKT2,Main            , 1
Up Type= 0
Dn Type= 3
Dn Slope=0.006517
Boundary for River Rch & Prof#=SNKNGCKT2,Main            , 2
Up Type= 0
Dn Type= 3
Dn Slope=0.006517
Boundary for River Rch & Prof#=SNKNGCKT2,Main            , 3
Up Type= 0
Dn Type= 3
Dn Slope=0.006517
Boundary for River Rch & Prof#=SNKNGCKT2,Main            , 4
Up Type= 0
Dn Type= 3
Dn Slope=0.006517
Boundary for River Rch & Prof#=SNKNGCKT2,Main            , 5
Up Type= 0
Dn Type= 3
Dn Slope=0.006517
Boundary for River Rch & Prof#=SNKNGCKT2,Main            , 6
Up Type= 0
Dn Type= 3
Dn Slope=0.006517
Boundary for River Rch & Prof#=SNKNGCKT3,Main            , 1
Up Type= 0
Dn Type= 3
Dn Slope=0.00548
Boundary for River Rch & Prof#=SNKNGCKT3,Main            , 2
Up Type= 0
Dn Type= 3
Dn Slope=0.00548
Boundary for River Rch & Prof#=SNKNGCKT3,Main            , 3
Up Type= 0
Dn Type= 3
Dn Slope=0.00548
Boundary for River Rch & Prof#=SNKNGCKT3,Main            , 4
Up Type= 0
Dn Type= 3
Dn Slope=0.00548
Boundary for River Rch & Prof#=SNKNGCKT3,Main            , 5
Up Type= 0
Dn Type= 3
Dn Slope=0.00548
Boundary for River Rch & Prof#=SNKNGCKT3,Main            , 6
Up Type= 0
Dn Type= 3
Dn Slope=0.00548
Boundary for River Rch & Prof#=SNKNGCKT4,Main            , 1
Up Type= 0
Dn Type= 3
Dn Slope=0.00461
Boundary for River Rch & Prof#=SNKNGCKT4,Main            , 2
Up Type= 0
Dn Type= 3
Dn Slope=0.00461
Boundary for River Rch & Prof#=SNKNGCKT4,Main            , 3
Up Type= 0
Dn Type= 3
Dn Slope=0.00461
Boundary for River Rch & Prof#=SNKNGCKT4,Main            , 4
Up Type= 0
Dn Type= 3
Dn Slope=0.00461
Boundary for River Rch & Prof#=SNKNGCKT4,Main            , 5
Up Type= 0
Dn Type= 3
Dn Slope=0.00461
Boundary for River Rch & Prof#=SNKNGCKT4,Main            , 6
Up Type= 0
Dn Type= 3
Dn Slope=0.00461
Boundary for River Rch & Prof#=STONYRN,Main            , 1
Up Type= 0
Dn Type= 3
Dn Slope=0.005293
Boundary for River Rch & Prof#=STONYRN,Main            , 2
Up Type= 0
Dn Type= 3
Dn Slope=0.005293
Boundary for River Rch & Prof#=STONYRN,Main            , 3
Up Type= 0
Dn Type= 3
Dn Slope=0.005293
Boundary for River Rch & Prof#=STONYRN,Main            , 4
Up Type= 0
Dn Type= 3
Dn Slope=0.005293
Boundary for River Rch & Prof#=STONYRN,Main            , 5
Up Type= 0
Dn Type= 3
Dn Slope=0.005293
Boundary for River Rch & Prof#=STONYRN,Main            , 6
Up Type= 0
Dn Type= 3
Dn Slope=0.005293
DSS Import GetInterval= 0
DSS Import GetPeak= 0
DSS Import FillOption= 0

--- SNKNGCKT2.g01 (geometry) ---

Geom Title=Geometry
Program Version=5.07

River Reach=SNKNGCKT2       ,Main
Reach XY= 30
2112348.11609414355861.2118966432112413.10940248355724.288614064
2112427.71403205355604.449942976 2112400.6028658355387.924129307
2112407.92798239 355319.629646482112376.84011805355293.205158651
2112361.81455755355186.9885075542112315.18276106355097.870247483
2112330.72669323355062.1193347282112330.20864964354991.135552809
2112345.75258181354968.8560698032112313.11025864 354933.62320064
2112367.51402122354865.2302928122112330.72669323354793.210095644
2112352.48813264354701.5012895612112328.13614722354700.983245984
2112298.60274172354673.5223428912112340.63546605354618.154999554
2112363.88771614354615.7071698162112375.20790347354553.293580726
2112349.81392539354525.4521009772112384.52875097354487.054539979
2112347.37429772354454.3728468122112399.68390439 354409.49695231
 2112348.8884023354383.5550750642112340.32969239354362.992452145
2112354.89790472354334.322890058 2112394.4493348354319.800281316
2112368.66493756354293.8180498032112371.20692723 354265.15898639

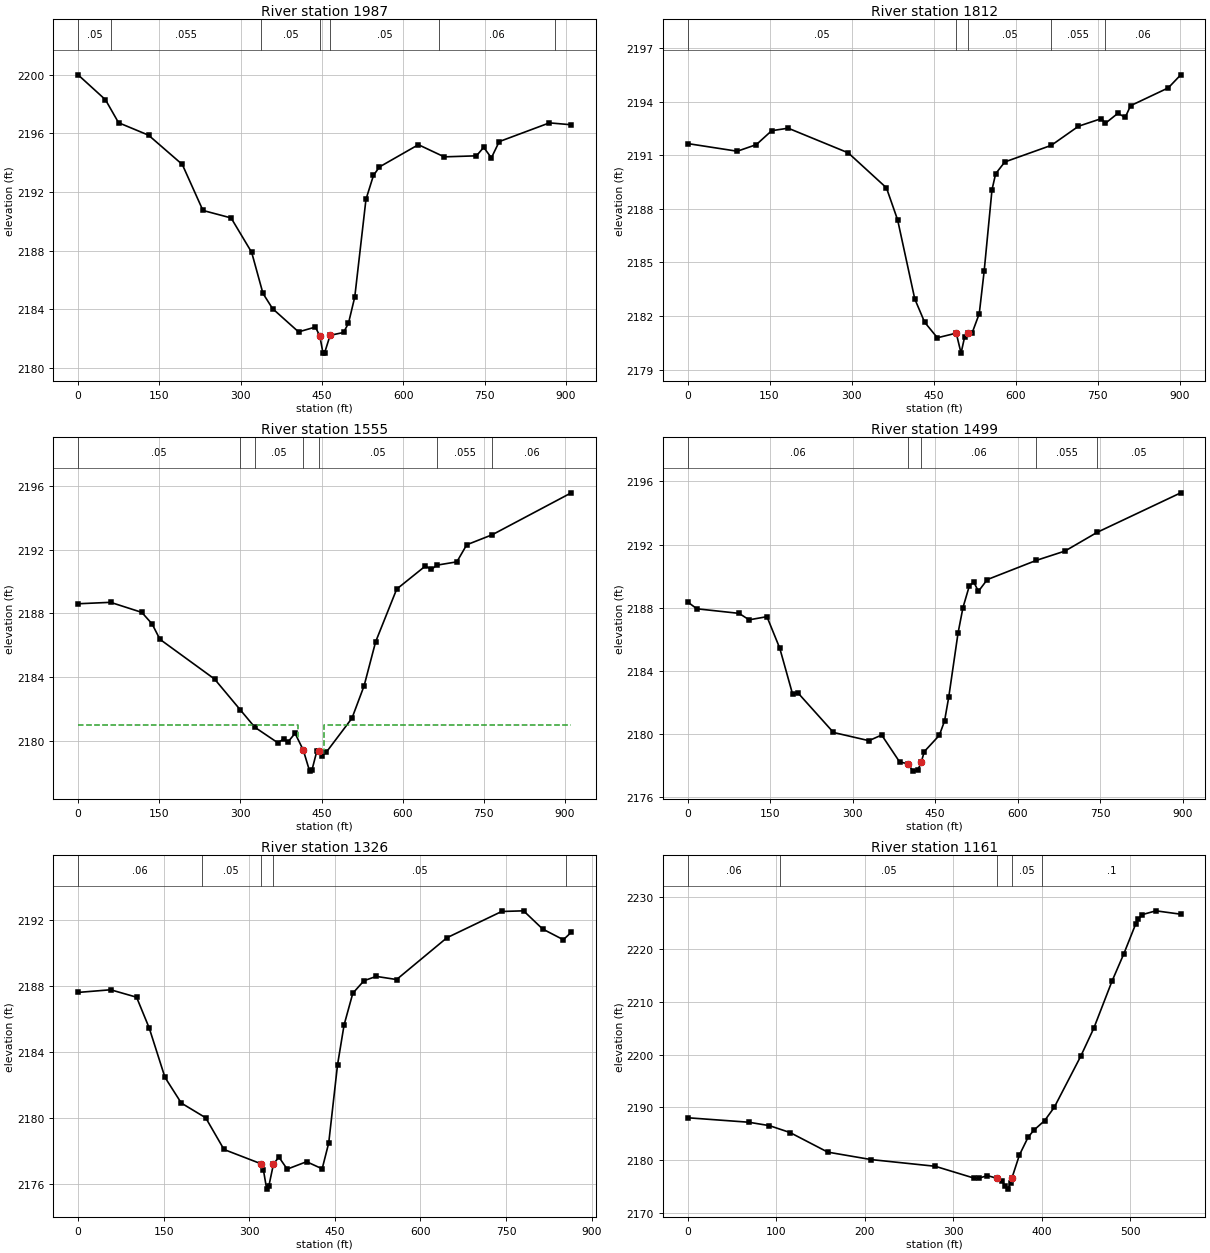
Type RM Length L Ch R = 1 ,1987    ,176.9,175,173.3
XS GIS Cut Line= 3
2112782.71496247355996.1460099822112351.24010363355851.711915642
2111919.00507572355709.596058145
#Sta/Elev= 30
       0    2200    50.5  2198.3    74.7 2196.73     130 2195.88   192.3 2193.88
   230.4 2190.74   282.3 2190.23   320.3 2187.88   341.1 2185.08   358.8 2184.04
   406.8 2182.45   437.9 2182.78     446 2182.17   451.8 2181.02   454.7    2181
  465.012182.216   489.8 2182.41   498.9 2183.04   510.5 2184.83   531.2  2191.5
     545 2193.13     556 2193.71   627.9 2195.23   675.6  2194.4     735 2194.47
   748.4 2195.05   762.6 2194.33     777 2195.44   869.7 2196.72     910 2196.59
#Mann= 7 ,-1 , 0
       0     .05       0   60.01    .055       0  338.03     .05       0
     446    .045       0  465.01     .05       0  666.66     .06       0
  879.13     .05       0
Bank Sta=446,465.01
XS Rating Curve= 0 ,0
Exp/Cntr=0.3,0.1

Type RM Length L Ch R = 1 ,1812    ,269.3,257.1,246.5
XS GIS Cut Line= 3
2112912.99980688355776.8964484782112333.46750139 355677.33562398
2112019.92547755355696.653498724
#Sta/Elev= 30
       0 2191.66    90.9 2191.23   125.8  2191.6   153.9 2192.38   184.1 2192.52
   293.9 2191.14   363.8 2189.18   384.3 2187.38   415.6 2182.96   433.7 2181.65
     457 2180.78   491.5 2181.04   500.3 2179.92     507 2180.85  513.19 2181.03
   520.3 2181.03   533.6 2182.13   542.6 2184.52   556.9 2189.07   563.6 2189.97
   580.4 2190.63   665.4 2191.56   715.1 2192.63   757.2 2193.06   764.2 2192.79
   787.4 2193.36   800.5 2193.12   810.4 2193.78   879.4 2194.78   902.2 2195.51
#Mann= 5 ,-1 , 0
       0     .05       0   491.5    .045       0  513.19     .05       0
   665.4    .055       0   764.2     .06       0
Bank Sta=491.5,513.19
XS Rating Curve= 0 ,0
Exp/Cntr=0.5,0.3

Type RM Length L Ch R = 1 ,1555    ,53.2,55.6,57.4
XS GIS Cut Line= 4
2112729.21539755 355142.070946472112389.82467213355459.446952149
2112270.57917573355573.1885225622112015.57771721355694.268660977
#Sta/Elev= 30
       0  2188.6      60 2188.69   117.8 2188.06   136.9 2187.33   151.3 2186.37
   252.2 2183.88   300.2 2181.93   326.8 2180.85   369.6 2179.87   380.1 2180.13
   387.5 2179.91   401.1 2180.47  416.352179.417     428  2178.1   432.5 2178.19
   441.4 2179.36  444.462179.352   450.4 2179.08   458.7 2179.28   506.3 2181.42
   528.7 2183.45     550 2186.21     589 2189.52   642.1 2190.97   653.1 2190.75
   662.9 2191.02   700.2 2191.23   718.4  2192.3   765.6 2192.93   911.7 2195.56
#Mann= 7 ,-1 , 0
       0     .05       0   300.2     .06       0   326.8     .05       0
  416.35    .045       0  444.46     .05       0   662.9    .055       0
   765.6     .06       0
#XS Ineff= 2 , 0
          406.35    2181  454.46            2181
Permanent Ineff=
       F       F
Bank Sta=416.35,444.46
XS Rating Curve= 0 ,0
Exp/Cntr=0.5,0.3

Type RM Length L Ch R = 1 ,1499    ,163.4,173.4,173.2
XS GIS Cut Line= 4
2112696.19348197355094.372879148 2112422.6264438355366.765707061
2112306.71985146355452.9525425582112011.00981297355668.419959396
#Sta/Elev= 30
       0 2188.37    16.8 2187.93    93.6 2187.64   111.9 2187.23   144.3 2187.43
   167.6 2185.43   190.8 2182.53   200.1 2182.62   265.2 2180.09   329.7 2179.57
   352.8 2179.93   385.3 2178.23  400.492178.099   409.9 2177.64   418.1 2177.68
   424.6  2178.2   430.3 2178.88   457.6 2179.91   467.1 2180.82   474.8 2182.35
   491.6 2186.39   500.6 2188.01   512.3  2189.4   520.3 2189.61   528.7 2189.04
   544.7 2189.78     634    2191     686 2191.59   744.7 2192.78   896.4 2195.28
#Mann= 5 ,-1 , 0
       0     .06       0  400.49    .045       0   424.6     .06       0
     634    .055       0   744.7     .05       0
Bank Sta=400.49,424.6
XS Rating Curve= 0 ,0
Exp/Cntr=0.5,0.3

Type RM Length L Ch R = 1 ,1326    ,151.5,164.2,162.2
XS GIS Cut Line= 3
2112678.32015814355100.8918949812112344.11905488355242.384722233
2111915.29937448355501.933415726
#Sta/Elev= 30
       0 2187.59    57.1 2187.75   102.5  2187.3   124.7 2185.43   152.2 2182.45
   180.9 2180.89   223.6    2180   255.7 2178.08   320.2 2177.22   324.9 2176.81
   330.5 2175.68   334.1 2175.84   342.4  2177.2   351.9 2177.62   366.4 2176.89
   400.4 2177.34   427.7 2176.91   439.2 2178.48   454.6  2183.2   466.1 2185.62
   481.4 2187.54     501  2188.3   522.5 2188.56   558.1 2188.37   646.3  2190.9
   742.2 2192.49   780.6 2192.53     814 2191.43   850.3 2190.78   864.2 2191.23
#Mann= 5 ,-1 , 0
       0     .06       0  216.29     .05       0   320.2    .045       0
   342.4     .05       0  855.24    .055       0
Bank Sta=320.2,342.4
XS Rating Curve= 0 ,0
Exp/Cntr=0.3,0.1

Type RM Length L Ch R = 1 ,1161    ,346.6,356.9,348.5
XS GIS Cut Line= 2
2112676.72895397355085.9155469832112119.48630205355096.317429066
#Sta/Elev= 30
       0 2188.03    69.1 2187.18    92.5 2186.53   115.8 2185.22   158.4  2181.5
   207.6 2180.08   279.9 2178.81   323.2 2176.59   329.1 2176.55   338.9 2177.04
  350.192176.498   355.3 2176.09   358.6 2175.06   361.9 2174.47   365.1 2175.72
   366.7 2176.67     375 2180.95   384.8 2184.33   391.4 2185.68   403.5 2187.49
   414.4 2190.02   444.2 2199.69     459 2205.02   479.6 2213.97   493.1 2219.23
   506.2 2224.76   509.5 2225.76   513.8 2226.62   529.2 2227.34   557.3  2226.7
#Mann= 5 ,-1 , 0
       0     .06       0  105.01     .05       0  350.19    .045       0
   366.7     .05       0  400.41      .1       0
Bank Sta=350.19,366.7
XS Rating Curve= 0 ,0
Exp/Cntr=0.3,0.1

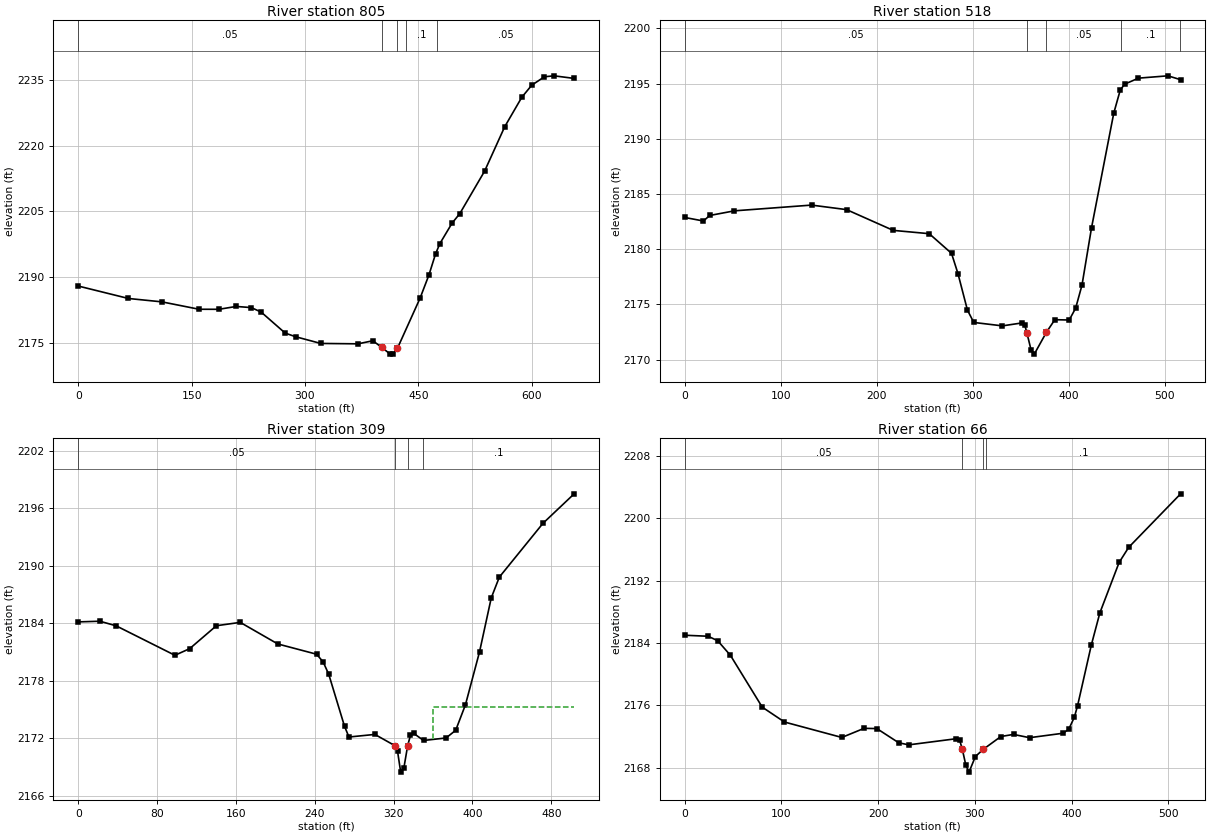
Type RM Length L Ch R = 1 ,805     ,287.65,286.5,282.74
XS GIS Cut Line= 2
2112743.59791473354781.289515808 2112088.2806558354813.981051475
#Sta/Elev= 30
       0 2187.95    66.4 2185.11   110.6 2184.34   159.9 2182.65   186.1 2182.64
   209.1 2183.29   228.9 2183.03     242 2182.01   273.8 2177.21   287.6 2176.38
   320.8 2174.85   370.1 2174.76   389.8 2175.46  401.482173.958   412.8 2172.41
   416.1 2172.48  422.272173.718   452.2 2185.16     464 2190.48   472.8 2195.31
   478.5 2197.65   494.7 2202.33   504.8 2204.47   537.6 2214.16   564.2 2224.29
   586.9 2231.04     600 2233.78   616.8 2235.71   629.6 2235.92   656.1 2235.33
#Mann= 5 ,-1 , 0
       0     .05       0  401.48    .045       0  422.27     .05       0
   433.9      .1       0  475.25     .05       0
Bank Sta=401.48,422.27
XS Rating Curve= 0 ,0
Exp/Cntr=0.3,0.1

Type RM Length L Ch R = 1 ,518     ,201.64,209.2,204.99
XS GIS Cut Line= 2
2112724.61632539 354658.015156062112213.22348687354585.511230266
#Sta/Elev= 30
       0 2182.87    19.5 2182.55    26.1 2183.05    51.8 2183.47   132.1 2183.99
   168.6 2183.58   217.2  2181.7   254.7  2181.4   277.9 2179.62   284.6 2177.79
   294.5 2174.47   301.1 2173.36   330.9 2173.05   350.8 2173.31   354.1 2173.15
   356.5 2172.38   360.8 2170.85   364.1 2170.49   376.8 2172.48   385.5 2173.61
   400.5 2173.58   407.2 2174.66   413.8 2176.75   423.7 2181.93   446.9 2192.33
   453.6  2194.4   458.1 2194.94   472.6 2195.49   503.3  2195.7   516.5 2195.35
#Mann= 5 ,-1 , 0
       0     .05       0   356.5    .045       0   376.8     .05       0
  454.35      .1       0  516.08      .1       0
Bank Sta=356.5,376.8
XS Rating Curve= 0 ,0
Exp/Cntr=0.3,0.1

Type RM Length L Ch R = 1 ,309     ,236.9,243.2,235.1
XS GIS Cut Line= 2
2112674.89398389354463.0247323962112171.81887455354451.325280726
#Sta/Elev= 30
       0 2184.14      22 2184.21    38.5 2183.73    98.1 2180.66   113.1 2181.35
   140.2 2183.74   164.4 2184.09   202.5 2181.84   241.9 2180.77   248.5 2179.97
   254.2 2178.68   270.2 2173.26   274.7 2172.14     301 2172.41   321.5 2171.23
     324 2170.66   327.2 2168.48   330.5 2168.96   334.3 2171.25   337.1 2172.31
   340.4 2172.52   350.4 2171.78   373.2 2172.04     383 2172.84   392.9  2175.5
   407.2 2181.02   419.1 2186.65   427.3 2188.81   471.6 2194.42   503.2 2197.49
#Mann= 4 ,-1 , 0
       0     .05       0   321.5    .045       0   334.3     .05       0
  349.65      .1       0
#XS Ineff= 2 , 0
                          359.59         2175.29
Permanent Ineff=
       F       F
Bank Sta=321.5,334.3
XS Rating Curve= 0 ,0
Exp/Cntr=0.3,0.1

Type RM Length L Ch R = 1 ,66      ,56.82,65.77,75.21
XS GIS Cut Line= 4
2112690.13247047354333.9898854792112423.35642922354312.882316142
2112356.08458214354314.8321153972112179.61839964354337.255955055
#Sta/Elev= 30
       0 2185.01    24.2 2184.88    34.1 2184.31    47.3 2182.43    80.2 2175.78
   103.2 2173.87   162.5 2171.89   185.5 2173.06   198.7 2173.03   221.3 2171.21
   231.6 2170.94   280.9 2171.73   284.2 2171.58  287.092170.379   290.7 2168.33
     294 2167.44   300.6 2169.44  308.612170.355   326.9 2172.01     340 2172.28
   356.6 2171.86   391.2 2172.43   397.1 2172.94   402.9 2174.48   406.2 2175.94
   420.5 2183.77   429.3 2187.88   449.2 2194.35   459.1 2196.29   512.8 2203.16
#Mann= 4 ,-1 , 0
       0     .05       0  287.09    .045       0  308.61     .05       0
  311.47      .1       0
Bank Sta=287.09,308.61
XS Rating Curve= 0 ,0
Exp/Cntr=0.3,0.1
LCMann Table=0

Chan Stop Cuts=-1
Use User Specified Reach Order=0
Composite Channel Slope=5